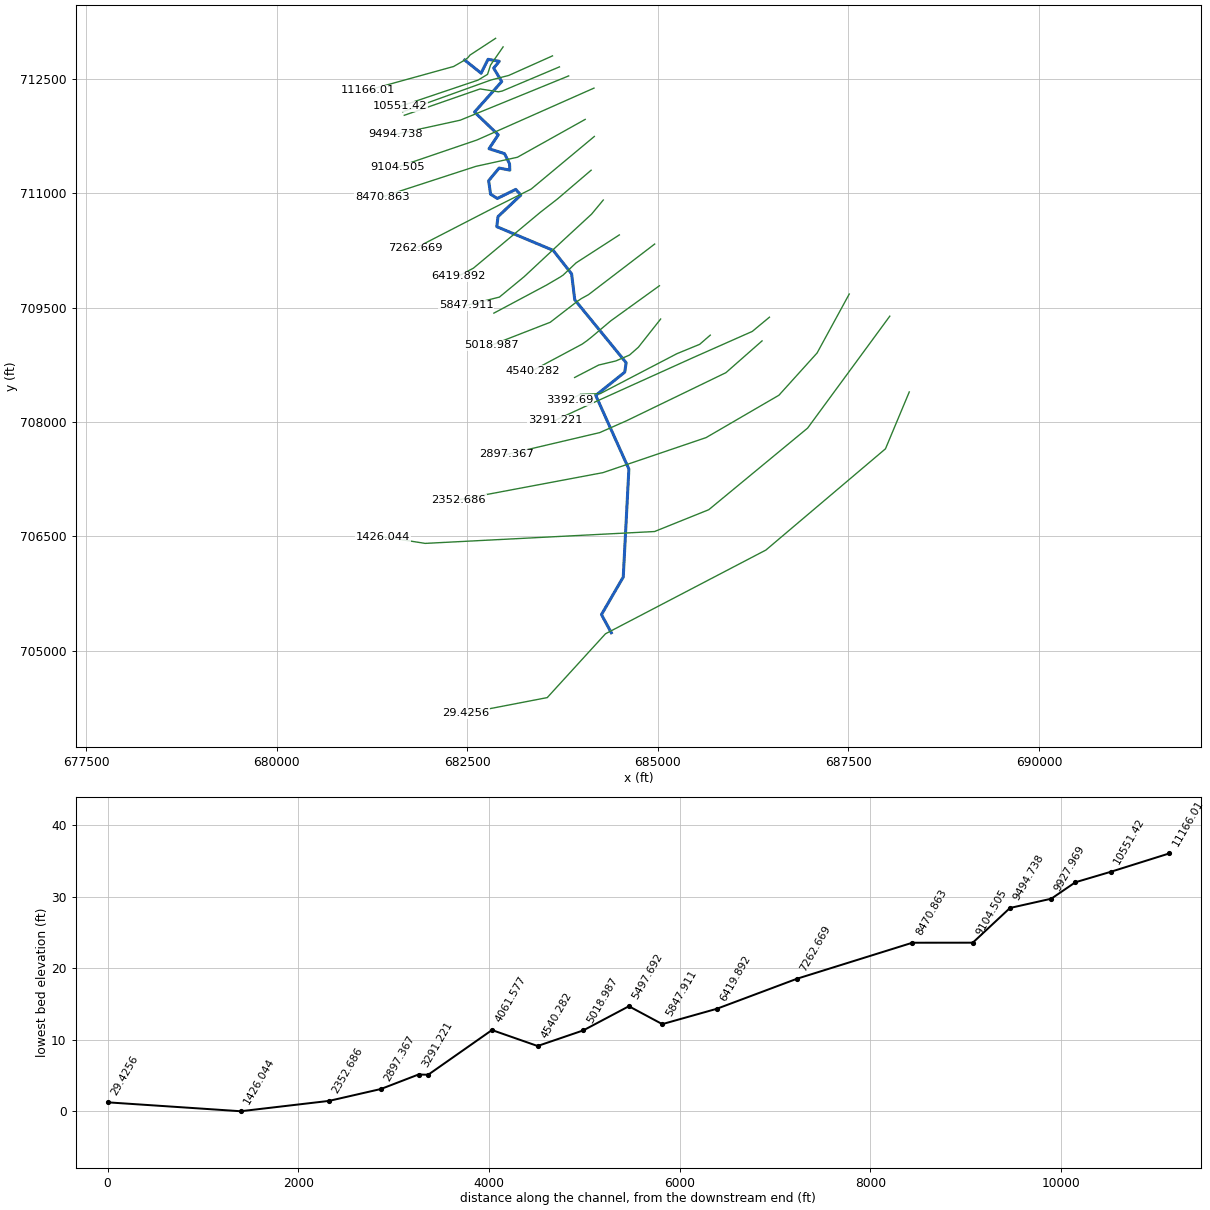
--- 4577_ras.prj (project) ---

Proj Title=4577
Current Plan=p01
Default Exp/Contr=0.3,0.1
English Units
Geom File=g01
Flow File=f01
Plan File=p01
Y Axis Title=Elevation
X Axis Title(PF)=Main Channel Distance
X Axis Title(XS)=Station
BEGIN DESCRIPTION:
RFD model 4577 exported to HEC-RAS
END DESCRIPTION:

--- 4577_ras.p01 (plan) ---

Plan Title=Plan 01
Program Version=4.10
Short Identifier=Plan 01
Geom File=g01
Flow File=f01
Subcritical Flow
Calc Critical at every XS
Secant Critical Depth

--- 4577_ras.f01 (steady flow) ---

Flow Title=Flow 01
Program Version=5.01
Number of Profiles= 6
Profile Names=10yr,25yr,50yr,100yr,100plus,500yr
River Rch & RM=4577,20,11166.01
 1319.91 2741.32 4396.12 6347.37 9267.1615646.12
River Rch & RM=4577,20,10551.42
 1321.39 2744.52 4401.37  6355.1 9278.4415663.27
River Rch & RM=4577,20,10180.36
 1368.21 2844.51 4564.73  6594.6 9628.1116188.15
River Rch & RM=4577,20,9927.969
 1377.76 2865.02 4598.37 6644.09 9700.3816297.22
River Rch & RM=4577,20,9494.738
 1452.06 3025.86 4863.38 7035.5310271.8817163.88
River Rch & RM=4577,20,9104.505
 1452.85 3027.57 4866.19 7039.6810277.9317172.98
River Rch & RM=4577,20,8470.863
 1455.67 3033.63 4876.17 7054.38 10299.417205.23
River Rch & RM=4577,20,7262.669
 1462.95 3049.38  4902.1 7092.6610355.2917289.46
River Rch & RM=4577,20,6419.892
  1495.5 3120.14 5019.01 7265.7610608.0217672.26
River Rch & RM=4577,20,5847.911
 1500.13 3130.14 5035.47 7290.0510643.4717725.39
River Rch & RM=4577,20,5497.692
 1501.25 3132.58 5039.49    729610652.1517738.46
River Rch & RM=4577,20,5018.987
 1502.31 3134.86 5043.26 7301.57 10660.317750.71
River Rch & RM=4577,20,4540.282
  1510.6 3152.83  5072.9 7345.3910724.2617846.96
River Rch & RM=4577,20,4061.577
 1511.87 3155.58 5077.43 7352.0810734.0317861.62
River Rch & RM=4577,20, 3392.69
 1568.19  3277.1 5277.31 7646.85 11164.418503.05
River Rch & RM=4577,20,2897.367
  1569.9 3280.84 5283.49    765611177.7618523.13
River Rch & RM=4577,20,2352.686
 1571.49 3284.29 5289.19 7664.4311190.0818541.59
River Rch & RM=4577,20,1426.044
 1583.46 3310.35  5332.3 7728.3511283.3918681.85
River Rch & RM=4577,20, 29.4256
 1635.78  3424.1 5520.28 8006.7111689.7919289.41
Boundary for River Rch & Prof#=4577,20,1
Up Type= 0
Dn Type= 2
Boundary for River Rch & Prof#=4577,20,2
Up Type= 0
Dn Type= 2
Boundary for River Rch & Prof#=4577,20,2
Up Type= 0
Dn Type= 2
Boundary for River Rch & Prof#=4577,20,2
Up Type= 0
Dn Type= 2
Boundary for River Rch & Prof#=4577,20,2
Up Type= 0
Dn Type= 2
Boundary for River Rch & Prof#=4577,20,2
Up Type= 0
Dn Type= 2

--- 4577_ras.g01 (geometry) ---

Geom Title=4577
Program Version=4.10

River Reach=4577,20
Reach XY= 30
682465.301885694712749.917233288682681.015083104712577.456861928
682772.160916418  712759.7485286682920.077583075712733.706861928
682846.119249731  712644.1235286682951.848416448  712467.5610286
682594.556749791712067.561028585682906.015083104711769.123528585
682785.181749791711586.831861928682988.306749761  711522.2485286
683053.931749761711388.915195242683058.098416448711306.102695242
682917.473416448  711333.1860286682779.973416448711167.040195242
682805.494249761710989.956861913682893.515083104710934.227695242
683135.702583075711053.498528585683201.848416448710977.977695242
682902.890083104710696.206861928682886.744249821710563.915195256
683626.848416418710252.977695242683868.515083075709945.165195242
683909.313694209709605.408250794684583.619249761708779.713806361
684565.563694239708655.408250794684185.008138627708350.547139704
684619.782444239707384.587938309684545.824110895705967.400438309
684260.114787579705475.048910201684389.574110895705236.497660518

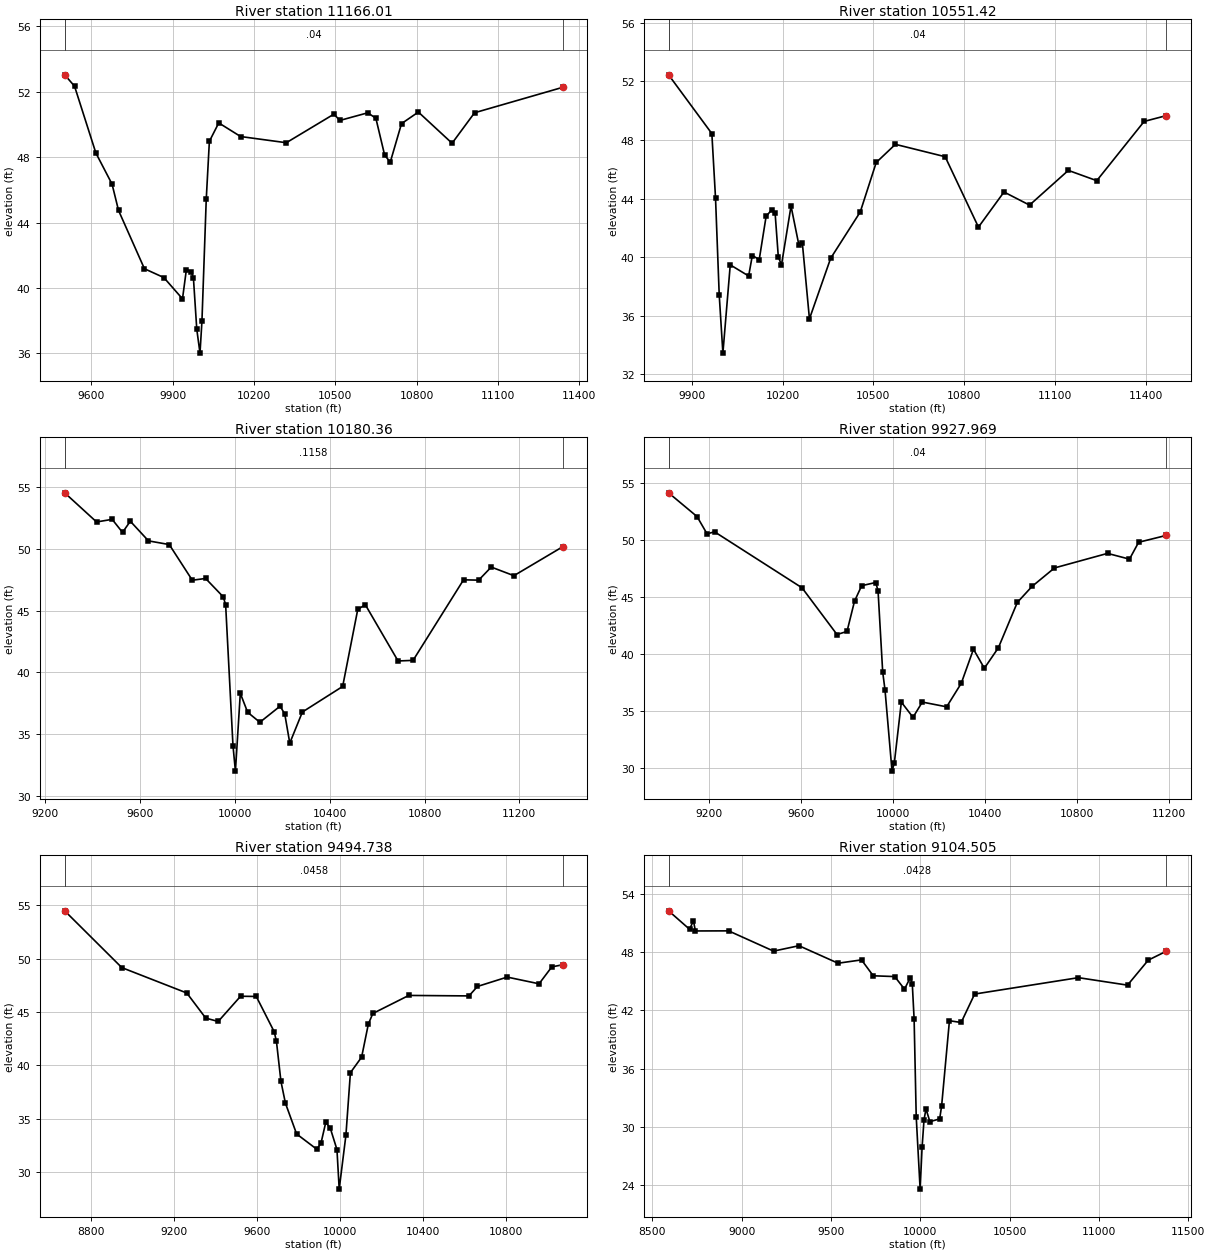
Type RM Length L Ch R = 1 ,11166.01,614.588600,614.588600,614.588600
XS GIS Cut Line= 6
682871.322416013713034.901762949 682534.97650986712815.083560305
 682509.17349204712782.525985341682470.929506875712752.137022684
682320.649063587712665.518814007681191.634916013712353.478151838
#Sta/Elev= 30
 9501.6853.037829538.05952.341269616.749  48.2579676.48146.353519700.37344.74476
9795.94341.18051 9867.6240.640419936.361 39.34059950.70541.124699968.56741.00691
9976.80240.592389989.05537.4784610000.9436.0200810008.1237.9665110024.0145.42576
10035.5548.9722510070.1650.0984310150.9249.2637910319.4748.88581 10495.750.63954
10516.4350.24576 10620.150.7158510649.9150.3813110682.29 48.126310703.0347.69909
10744.4950.0533210806.6950.7610610931.08  48.85411014.0150.7179911338.8652.27128
#Mann= 3 , 0 , 0
 9501.68    0.04       0 9501.68    0.04       011338.86    0.04       0
#XS Ineff= 2 , 0
       0                10120.56       0
Bank Sta=9501.68,11338.86
Exp/Cntr=0.3,0.1

Type RM Length L Ch R = 1 ,10551.42,371.059600,371.059600,371.059600
XS GIS Cut Line= 5
682969.762209356712922.661357924682804.831653804712683.946080118
682765.769153774712562.418302357682639.901098222712486.463441238
681616.322703766712141.432002616
#Sta/Elev= 30
9823.14352.447159966.15648.434589978.31144.022069990.46537.4302810002.6233.45113
10026.9339.47621 10087.738.7163410099.8640.1144410122.6939.8392110145.4242.79028
10164.7143.2533910175.2142.9876710185.7140.0232410196.2239.4723210227.7343.48712
10253.5240.84728 10265.240.9490210288.5635.7894710358.6439.9235310456.44 43.0881
10509.2146.4642410572.52 47.702810736.9146.85828 10846.942.0530110931.32  44.449
11015.7443.5544611143.8945.9245211237.8145.2228611394.3449.2661311468.1249.66541
#Mann= 3 , 0 , 0
9823.143    0.04       09823.143    0.04       011468.12    0.04       0
#XS Ineff= 2 , 0
       0                10611.17       0
Bank Sta=9823.143,11468.12
Exp/Cntr=0.3,0.1

Type RM Length L Ch R = 1 ,10180.36,252.390900,252.390900,252.390900
XS GIS Cut Line= 4
 683617.85019379712804.867040727683043.967316159712548.222313019
682811.342070431712488.633580118681651.704360457712071.360096282
#Sta/Elev= 30
9281.46354.554089416.03952.191569481.76552.403749525.583 51.34619558.44652.24982
9635.12750.658279722.76250.359629820.03147.467869876.12447.611099950.344 46.1267
9960.66745.489829991.63634.0673110001.9631.98986 10022.638.2989710053.57  36.761
10105.1935.9517510190.52 37.256110210.1336.6296610231.3934.2620810284.5336.78142
10454.5738.8559510518.3445.1096910550.2245.4796410688.3840.9211710751.6940.97019
 10964.747.5012111028.47 47.4734 11081.648.5346511177.2547.8362411382.6850.17607
#Mann= 3 , 0 , 0
9281.463  0.1158       09281.463  0.1158       011382.68  0.1158       0
#XS Ineff= 2 , 0
       09913.761        10570.38       0
Bank Sta=9281.463,11382.68
Exp/Cntr=0.3,0.1

Type RM Length L Ch R = 1 ,9927.969,433.231100,433.231100,433.231100
XS GIS Cut Line= 5
683709.004020269712660.454888589 682958.06568486712343.566756753
682907.954999909  712333.3993714682668.588280807712371.318851654
681673.201924146712025.303594339
#Sta/Elev= 30
9026.41554.141529150.15452.05533 9193.5750.537319226.13150.717079606.01945.79869
9757.97341.693079801.38941.969659833.95144.622929865.01345.984929925.97546.26477
  9936.1 45.55249956.34938.403989966.47436.817149996.84829.6970510006.9730.43613
10037.35 35.757610087.9734.4261410128.4735.7624910234.0435.3447210297.5637.41097
 10350.540.4030410397.8538.7326810458.7640.5330210541.0644.5174510604.5945.91421
10702.4147.5435410932.7848.8224811028.0648.3167411067.8849.7986811188.7750.40578
#Mann= 3 , 0 , 0
9026.415    0.04       09026.415    0.04       011188.77    0.04       0
#XS Ineff= 2 , 0
       09868.944        10415.08       0
Bank Sta=9026.415,11188.77
Exp/Cntr=0.3,0.1

Type RM Length L Ch R = 1 ,9494.738,390.233000,390.233000,390.233000
XS GIS Cut Line= 3
683829.872363578712541.956512796682407.056043442711960.991451415
681564.183418417711776.457005173
#Sta/Elev= 30
8671.17254.466268946.47349.148539259.71746.769819350.91244.420329410.93844.10264
9518.95346.466499594.56446.445769680.97643.139669691.777 42.2394 9713.3838.49964
9734.98336.454979788.99133.568289886.20432.137659906.43632.70528 9929.4134.65537
9951.01334.125969983.41832.107239994.21928.4024810026.6233.4606210048.2339.30775
10102.2340.7596210134.6443.8549510156.2444.8516410329.5646.5422510619.6146.49753
10660.5647.3834310803.8748.2609210957.42 47.632711018.8549.2141711070.8749.41412
#Mann= 3 , 0 , 0
8671.172  0.0458       08671.172  0.0458       011070.87  0.0458       0
#XS Ineff= 2 , 0
       0                               0
Bank Sta=8671.172,11070.87
Exp/Cntr=0.3,0.1

Type RM Length L Ch R = 1 ,9104.505,633.642400,633.642400,633.642400
XS GIS Cut Line= 3
684162.303270831712382.157556381682626.526332908711701.166100054
681578.567082986711343.943928388
#Sta/Elev= 30
8591.09552.281998708.47550.381718730.353  51.2548741.29250.203978927.25550.21403
9178.85248.123549321.05948.680239539.83946.873699671.10847.218079736.74245.57797
9857.07145.496049911.76644.198139944.58345.399599955.52244.704339965.58941.11043
  9977.431.015989999.27823.5566910010.2227.8767710021.1630.7317410032.09 31.8332
10053.9730.5195110108.6730.8075310119.6132.1508210163.3640.93855   1022940.75681
10304.3943.6922510885.4745.3835711160.1644.6116911276.3747.1934711378.25 48.1185
#Mann= 3 , 0 , 0
8591.095  0.0428       08591.095  0.0428       011378.25  0.0428       0
#XS Ineff= 2 , 0
       0                               0
Bank Sta=8591.095,11378.25
Exp/Cntr=0.3,0.1

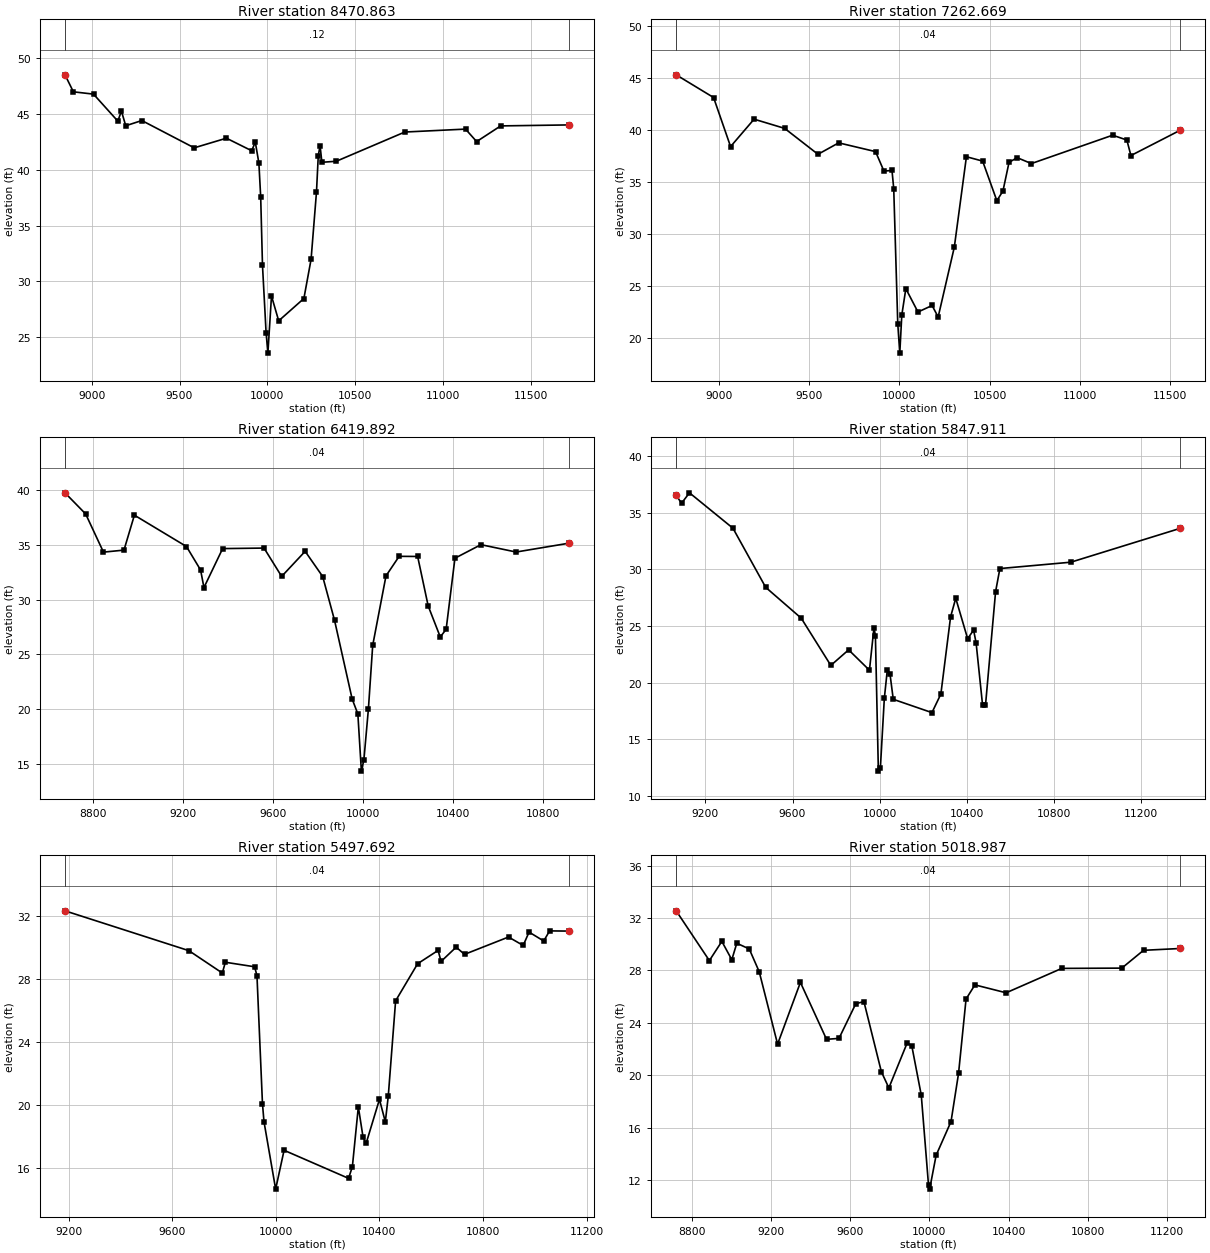
Type RM Length L Ch R = 1 ,8470.863,1208.193600,1208.193600,1208.193600
XS GIS Cut Line= 4
684046.669638235711971.533707393683157.594950012711474.877076576
682613.526015367711355.629090894681385.211304901710955.908707393
#Sta/Elev= 30
 8848.5448.53424 8896.2747.009029010.81546.801049149.00644.379279169.51145.27967
9194.08743.962769285.72344.430699583.54141.980549766.81342.846039910.53741.71888
9931.01242.495159951.487 40.60969961.724 37.56619971.96231.425629992.43625.39808
10002.6723.5515610023.1528.68452 10064.126.4517310207.42 28.453610248.37 31.9739
10279.08 38.015810289.3241.2901110299.5642.16853 10309.8 40.684110391.6940.77397
10781.4243.3988411126.9543.6619711190.0542.5410711326.7643.9488211715.6344.03756
#Mann= 3 , 0 , 0
 8848.54    0.12       0 8848.54    0.12       011715.63    0.12       0
#XS Ineff= 2 , 0
       0                               0
Bank Sta=8848.54,11715.63
Exp/Cntr=0.3,0.1

Type RM Length L Ch R = 1 ,7262.669,842.776900,842.776900,842.776900
XS GIS Cut Line= 4
684166.461304902 711747.57537406683337.319376886711056.899640145
682833.043459326710804.605802342681812.294638235 710278.82537406
#Sta/Elev= 30
8764.87845.283278972.01643.101499066.124 38.38599196.273 41.02139365.46840.13626
9550.11137.645499664.81238.744679868.95937.902659915.29736.033479959.996 36.0904
9969.59534.349459991.95821.3435810003.1418.5339510014.3222.1946510036.6924.73077
10103.7822.4860810182.05  23.11210215.5922.0068110305.0528.7143810372.1437.41142
10461.91 36.991310540.6533.18605 10574.434.1148710608.1436.8712910653.1437.32029
10731.8836.7534911181.8339.4804211260.5739.0161211283.0637.5250711556.0739.95755
#Mann= 3 , 0 , 0
8764.878    0.04       08764.878    0.04       011556.07    0.04       0
#XS Ineff= 2 , 0
       0                10439.84       0
Bank Sta=8764.878,11556.07
Exp/Cntr=0.3,0.1

Type RM Length L Ch R = 1 ,6419.892,571.981700,571.981700,571.981700
XS GIS Cut Line= 5
684124.794638235711304.867040727683682.293252205710927.134481222
683458.127971568710752.783707393682580.828313003710020.039106206
682380.002971568709914.242040727
#Sta/Elev= 30
8677.89739.756468769.66337.823078848.55134.338498939.53334.52248 8985.7437.71519
9216.77634.850469279.46132.702469294.27331.10047 9377.1934.661149560.787 34.7096
9638.96232.119499743.19634.411479821.018 32.11099873.48828.117299951.66320.92135
9977.01419.550669992.61314.3301110003.7815.3654310023.8120.0128810042.8725.81833
10101.8132.1673910160.13 33.954410242.2133.9421110289.0129.4167810342.5426.58853
 10368.6 27.284810407.6933.78437   1052335.01968   1067934.3479410913.7235.15561
#Mann= 3 , 0 , 0
8677.897    0.04       08677.897    0.04       010913.72    0.04       0
#XS Ineff= 2 , 0
       09758.147         10123.6       0
Bank Sta=8677.897,10913.72
Exp/Cntr=0.3,0.1

Type RM Length L Ch R = 1 ,5847.911,350.219100,350.219100,350.219100
XS GIS Cut Line= 6
684283.966965308710913.925779786 684130.76421023710729.055824227
683746.255299984 710374.28807123683247.128610414709908.936871932
682921.575066636709640.433538857682486.977997401709530.697296926
#Sta/Elev= 30
9065.379 36.54069089.95935.842769126.44836.762069326.207 33.63769476.59628.41837
9639.87125.695059775.93321.52173 9857.7122.897059953.41421.095689974.249 24.8634
9980.75824.14363 9994.4312.1875310003.58  12.45810021.77 18.617610035.4521.11359
10047.57 20.799510062.7918.5300910240.5317.3534510281.5418.9948610326.19 25.8074
 10349.927.4524510404.5923.8796710431.9324.6452610443.5123.5063610472.9518.05611
10486.6218.0030510532.9628.03214 10552.730.0749410878.7230.6364211381.2933.62568
#Mann= 3 , 0 , 0
9065.379    0.04       09065.379    0.04       011381.29    0.04       0
#XS Ineff= 2 , 0
       09791.658         10348.7       0
Bank Sta=9065.379,11381.29
Exp/Cntr=0.3,0.1

Type RM Length L Ch R = 1 ,5497.692,478.704700,478.704700,478.704700
XS GIS Cut Line= 6
684494.586304902710455.908707393683927.649780668710089.680601081
683756.381579474709928.240876052683719.837209121709903.917930111
683540.438602086709798.597874031682848.752971568709429.867040727
#Sta/Elev= 30
9185.244 32.34189663.81929.814959793.07728.394599804.61329.079469917.84428.79194
9926.867 28.22259948.11420.103279953.95318.96836    999914.6861210031.5817.15068
10280.6115.3706510295.4116.1095710318.4519.9078710336.7917.9675510348.5217.58882
10400.0220.3777910422.6818.9557810434.01 20.569510462.46 26.632610547.4928.98574
10626.6629.8315310637.9929.1295410696.2930.0367610728.6529.5796810898.6330.67992
10955.2930.1451710977.9630.9923911034.6230.4273811057.2831.0688711132.3631.05626
#Mann= 3 , 0 , 0
9185.244    0.04       09185.244    0.04       011132.36    0.04       0
#XS Ineff= 2 , 0
       09782.059        10311.93       0
Bank Sta=9185.244,11132.36
Exp/Cntr=0.3,0.1

Type RM Length L Ch R = 1 ,5018.987,478.704700,478.704700,478.704700
XS GIS Cut Line= 6
684958.127971568710336.117040727684090.934501529709672.903644223
683997.287295301709621.082327319683944.785110647709585.656204995
683588.336304902 709310.07537406682812.294638235709007.992040727
#Sta/Elev= 30
8721.24832.546128888.84628.748848951.79230.213989002.149 28.81589027.32830.07286
9090.27429.636929140.63127.897099233.38522.373769348.61427.085949480.54122.74065
9543.48722.814289628.45525.464689669.37925.617519757.50420.266799795.27219.03513
9887.88422.47113 9911.0922.248699958.98918.482449995.53211.6276910001.3111.31173
10033.9713.8934410109.2816.4683310147.2320.1408410185.1825.8154710229.9326.89565
10387.5626.2921810668.4728.1532310971.7128.1746111081.3729.53375 11266.729.67244
#Mann= 3 , 0 , 0
8721.248    0.04       08721.248    0.04       0 11266.7    0.04       0
#XS Ineff= 2 , 0
       09913.375                       0
Bank Sta=8721.248,11266.7
Exp/Cntr=0.3,0.1

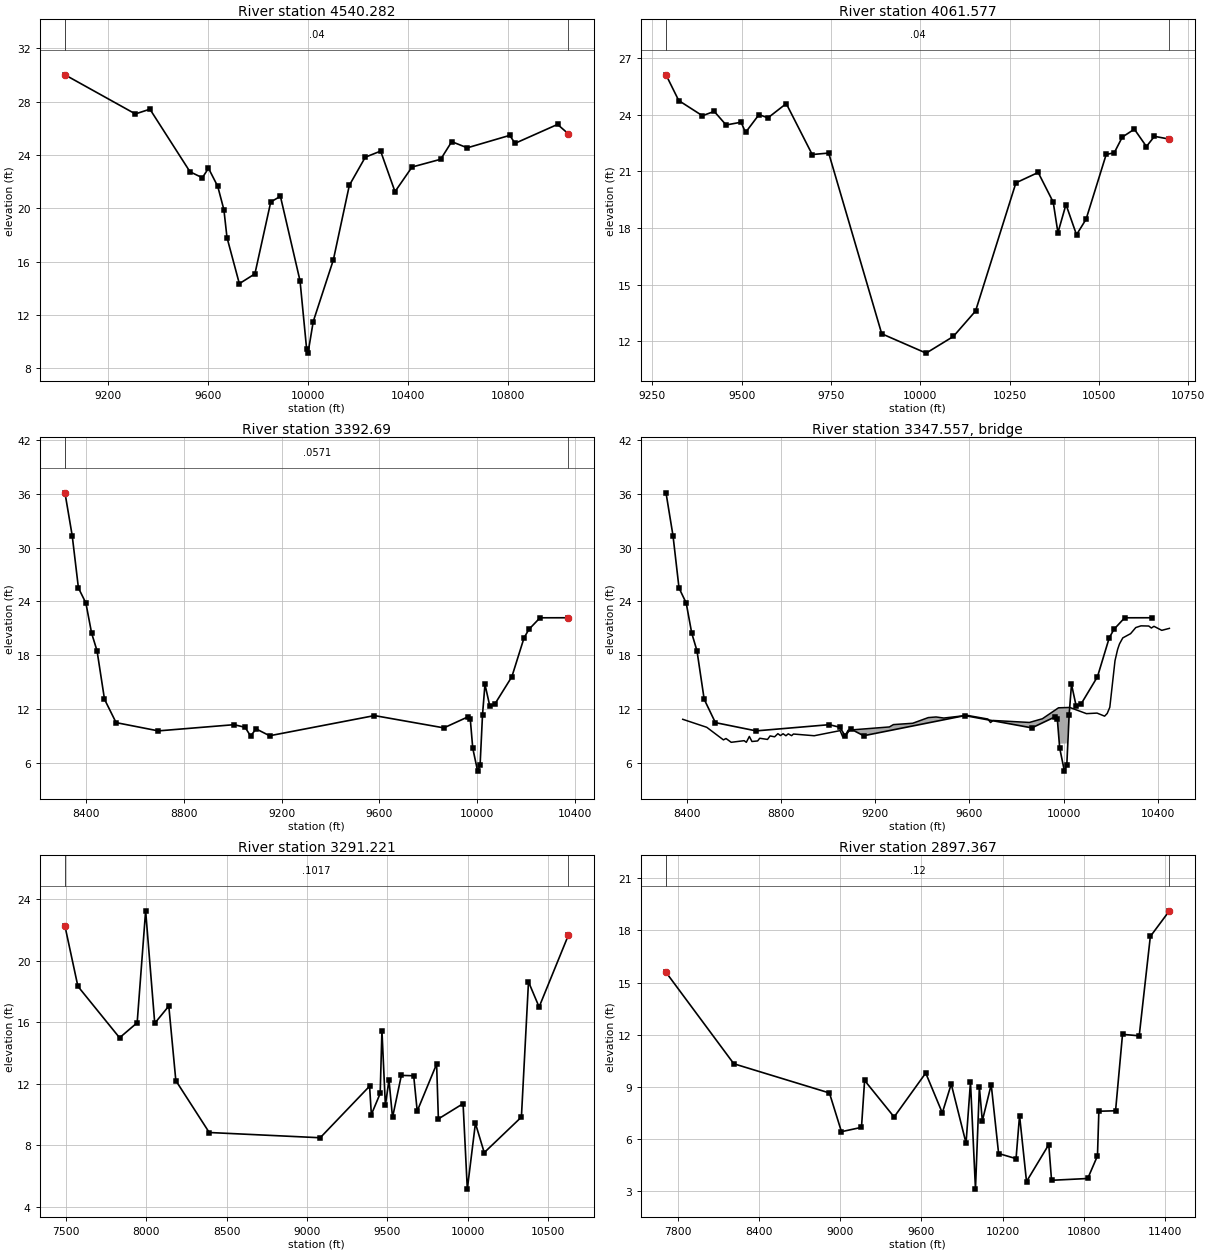
Type RM Length L Ch R = 1 ,4540.282,478.704700,478.704700,478.704700
XS GIS Cut Line= 6
685020.627971568709789.242040727684381.862977873709328.335927434
684134.797182656709119.779145635684067.903402905   709066.678371
684007.100463876709023.502120357683353.961304902708674.658707393
#Sta/Elev= 30
9029.85830.003189311.16627.07018 9369.3627.426259529.48622.734029578.75522.28644
 9603.3922.997349640.34221.638819664.977 19.88579677.29517.803719726.66514.34456
9788.80115.079069852.15320.471469890.791 20.89169969.18714.554319995.5489.432398
   100019.13516610021.9311.5032910102.2216.1208510166.1821.7181410229.8723.82639
 10291.224.2837410348.6221.2423810416.64 23.088510531.1923.6709310575.3524.99343
10637.33 24.529510807.13 25.463410828.3624.8672710998.1726.2850211041.3525.57797
#Mann= 3 , 0 , 0
9029.858    0.04       09029.858    0.04       011041.35    0.04       0
#XS Ineff= 2 , 0
       09880.456        10264.74       0
Bank Sta=9029.858,11041.35
Exp/Cntr=0.3,0.1

Type RM Length L Ch R = 1 ,4061.577,668.887300,668.887300,668.887300
XS GIS Cut Line= 6
 685036.50289923709352.634006411684744.497971207708982.547549278
684627.765276313708879.548112616 684448.61831373708802.446888208
684223.492487431708748.845500991683907.853373975 708585.40497376
#Sta/Elev= 30
9287.94226.116239323.58924.752289389.90123.946489422.892 24.17829456.21223.45734
 9498.1223.604289510.65823.061359548.272  24.0079573.34723.834939624.61424.59116
9697.31721.890159743.41421.969069891.87412.3894610016.2211.3625810092.43 12.2459
10154.6113.5942310267.6520.3907310329.9720.9401310372.0319.3683110385.2717.74607
10407.7919.2408410437.2817.63885 10464.118.46274 10520.421.8951410542.92 21.9834
10565.4522.8154310599.2323.2345710633.0122.3161310655.5322.8560410697.37 22.7067
#Mann= 3 , 0 , 0
9287.942    0.04       09287.942    0.04       010697.37    0.04       0
#XS Ineff= 2 , 0
       09714.215           10122       0
Bank Sta=9287.942,10697.37
Exp/Cntr=0.3,0.1

Type RM Length L Ch R = 1 , 3392.69,101.468800,101.468800,101.468800
XS GIS Cut Line= 6
685687.439841986709141.157748029685548.329034835709020.384882092
685250.219839603708897.970301986684242.773479223708373.162659869
683984.791541398708364.829326525683841.449263901708291.104428262
#Sta/Elev= 30
8312.99436.094348342.71131.318338368.14825.505328398.655 23.83038422.16820.47465
8444.41618.509418474.92313.119428522.43610.519398695.4019.6004829005.67610.29083
9050.7549.9977769073.2949.0276929095.8339.8226769151.2339.0584699580.72811.30271
9864.9569.9351339963.20211.156889973.20410.873219983.2067.67630210003.215.121522
10013.215.76875610023.2211.3980610033.2214.7772910053.2312.3410610073.2312.56533
10143.3515.62442 10193.419.95987 10213.620.9100110258.7822.1868810374.8222.19092
#Mann= 3 , 0 , 0
8312.994  0.0571       08312.994  0.0571       010374.82  0.0571       0
#XS Ineff= 2 , 0
       09130.919        10079.18       0
Bank Sta=8312.994,10374.82
Exp/Cntr=0.3,0.1

Type RM Length L Ch R = 3 ,3347.557,,,
BEGIN DESCRIPTION:
END DESCRIPTION:
Bridge Culvert--1,0,-1,-1, 0
Deck Dist Width WeirC Skew NumUp NumDn MinLoCord MaxHiCord MaxSubmerge Is_Ogee
34.194400,33.080000,2.6,0, 60, 60, , , 0.95, 0, 0,0,,
 8383.96 8485.75 8556.57 8567.57 8589.57 8644.57 8653.73 8666.57 8677.57 8701.73
 8710.58 8743.58 8754.58 8773.72 8787.58 8798.58 8809.58 8821.72 8831.58 8845.72
 8853.58 8941.71 9051.59 9062.59 9073.59 9085.69 9260.60 9277.68 9359.61 9425.61
 9458.62 9491.62 9590.62 9678.63 9689.63 9700.63 9854.64 9909.64 9978.14 9978.14
10026.5210035.7610035.7610096.6510141.5710173.7110184.7310195.7510217.7910228.80
10236.8310250.8410283.9010305.9310327.9710361.0310372.0410383.0610416.1210448.59
   10.89   10.00    8.60    8.75    8.33    8.51    8.33    8.98    8.42    8.48
    8.78    8.65    9.04    8.94    9.29    9.08    9.28    9.06    9.27    9.07
    9.25    9.06    9.63    8.94    9.09    9.68   10.04   10.30   10.45   11.08
   11.15   11.03   11.33   10.92   10.53   10.76   10.54   10.95   12.17   12.17
   12.21   12.11   12.11   11.52   11.58   11.24   11.54   12.23   17.41   18.66
   19.28   19.95   20.42   21.10   21.29   21.27   21.05   21.24   20.79   21.01
 -989.11 -990.00 -991.40 -991.25 -991.67 -991.49 -991.67 -991.02 -991.58 -991.52
 -991.22 -991.35 -990.96 -991.06 -990.71 -990.92 -990.72 -990.94 -990.73 -990.93
 -990.75 -990.94 -990.37 -991.06 -990.91 -990.32 -989.96 -989.70 -989.55 -988.92
 -988.85 -988.97 -988.67 -989.08 -989.47 -989.24 -989.46 -989.05 -987.83    8.17
    8.21    8.11 -987.89 -988.48 -988.42 -988.76 -988.46 -987.77 -982.59 -981.34
 -980.72 -980.05 -979.58 -978.90 -978.71 -978.73 -978.95 -978.76 -979.21 -978.99
 8383.96 8485.75 8556.57 8567.57 8589.57 8644.57 8653.73 8666.57 8677.57 8701.73
 8710.58 8743.58 8754.58 8773.72 8787.58 8798.58 8809.58 8821.72 8831.58 8845.72
 8853.58 8941.71 9051.59 9062.59 9073.59 9085.69 9260.60 9277.68 9359.61 9425.61
 9458.62 9491.62 9590.62 9678.63 9689.63 9700.63 9854.64 9909.64 9970.95 9970.95
10026.5210028.5710028.5710096.6510141.5710173.7110184.7310195.7510217.7910228.80
10236.8310250.8410283.9010305.9310327.9710361.0310372.0410383.0610416.1210448.59
   10.89   10.00    8.60    8.75    8.33    8.51    8.33    8.98    8.42    8.48
    8.78    8.65    9.04    8.94    9.29    9.08    9.28    9.06    9.27    9.07
    9.25    9.06    9.63    8.94    9.09    9.68   10.04   10.30   10.45   11.08
   11.15   11.03   11.33   10.92   10.53   10.76   10.54   10.95   12.12   12.12
   12.21   12.18   12.18   11.52   11.58   11.24   11.54   12.23   17.41   18.66
   19.28   19.95   20.42   21.10   21.29   21.27   21.05   21.24   20.79   21.01
 -989.11 -990.00 -991.40 -991.25 -991.67 -991.49 -991.67 -991.02 -991.58 -991.52
 -991.22 -991.35 -990.96 -991.06 -990.71 -990.92 -990.72 -990.94 -990.73 -990.93
 -990.75 -990.94 -990.37 -991.06 -990.91 -990.32 -989.96 -989.70 -989.55 -988.92
 -988.85 -988.97 -988.67 -989.08 -989.47 -989.24 -989.46 -989.05 -987.88    8.12
    8.21    8.18 -987.82 -988.48 -988.42 -988.76 -988.46 -987.77 -982.59 -981.34
 -980.72 -980.05 -979.58 -978.90 -978.71 -978.73 -978.95 -978.76 -979.21 -978.99
BR Coef=-1 , 0 , 0 ,, 0 ,,,0.8,0,1,0,
WSPro=,,,, 1 ,,,, 0 ,,,, 0 ,,,,-1 ,-1 ,-1 , 0 , 0 , 0 , 0 , 0
BC Design=,, 0 ,, 0 ,,,,,,

Type RM Length L Ch R = 1 ,3291.221,393.854900,393.854900,393.854900
XS GIS Cut Line= 5
686463.607720256709376.360135391686238.485435188709189.878242567
685464.646362066708847.170782864684118.813028693708238.837449566
683649.827118248708022.062712014
#Sta/Elev= 30
7494.11722.258727574.629 18.34427834.00414.997817943.37215.975057996.05523.25315
 8052.74 15.94118140.23417.060648183.98112.21258 8391.788.8379989082.3278.496534
9389.60211.851349400.57610.007349455.44711.377649466.421 15.46569487.78910.60757
9510.31812.250199532.2669.8135869587.13712.551099663.95612.529389685.90410.22976
9806.61913.290779817.5939.7219599971.23110.714199997.635 5.1557510048.059.436908
10102.927.53084610334.249.84106510378.31 18.637610444.4116.9994410626.3721.66547
#Mann= 3 , 0 , 0
7494.117  0.1017       07494.117  0.1017       010626.37  0.1017       0
#XS Ineff= 2 , 0
       09059.882        10080.01       0
Bank Sta=7494.117,10626.37
Exp/Cntr=0.3,0.1

Type RM Length L Ch R = 1 ,2897.367,544.680100,544.680100,544.680100
XS GIS Cut Line= 5
686366.921974599709065.505281642685892.963641256 708648.83861497
684590.880307913708018.630281642684236.713641256707862.380281642
683017.963641286707575.921948299
#Sta/Elev= 30
7714.48415.591328215.05510.337778920.9958.6601139009.8726.4351459157.7516.684141
9180.7059.3793619398.7127.2795019632.0169.8043559754.5547.5140079820.4169.171605
9929.7155.7767439962.5059.2884259999.3193.13456310028.088.99337510049.947.056965
10115.529.14028910170.175.181085 10298.94.88651110324.81 7.3627310376.17  3.5699
10540.535.69436110561.073.64220810828.163.74527110900.075.04518310910.347.610898
11033.617.63564911084.97 12.027811208.2411.9445311290.4217.6533411431.19 19.1255
#Mann= 3 , 0 , 0
7714.484    0.12       07714.484    0.12       011431.19    0.12       0
#XS Ineff= 2 , 0
       08918.125        10524.24       0
Bank Sta=7714.484,11431.19
Exp/Cntr=0.3,0.1

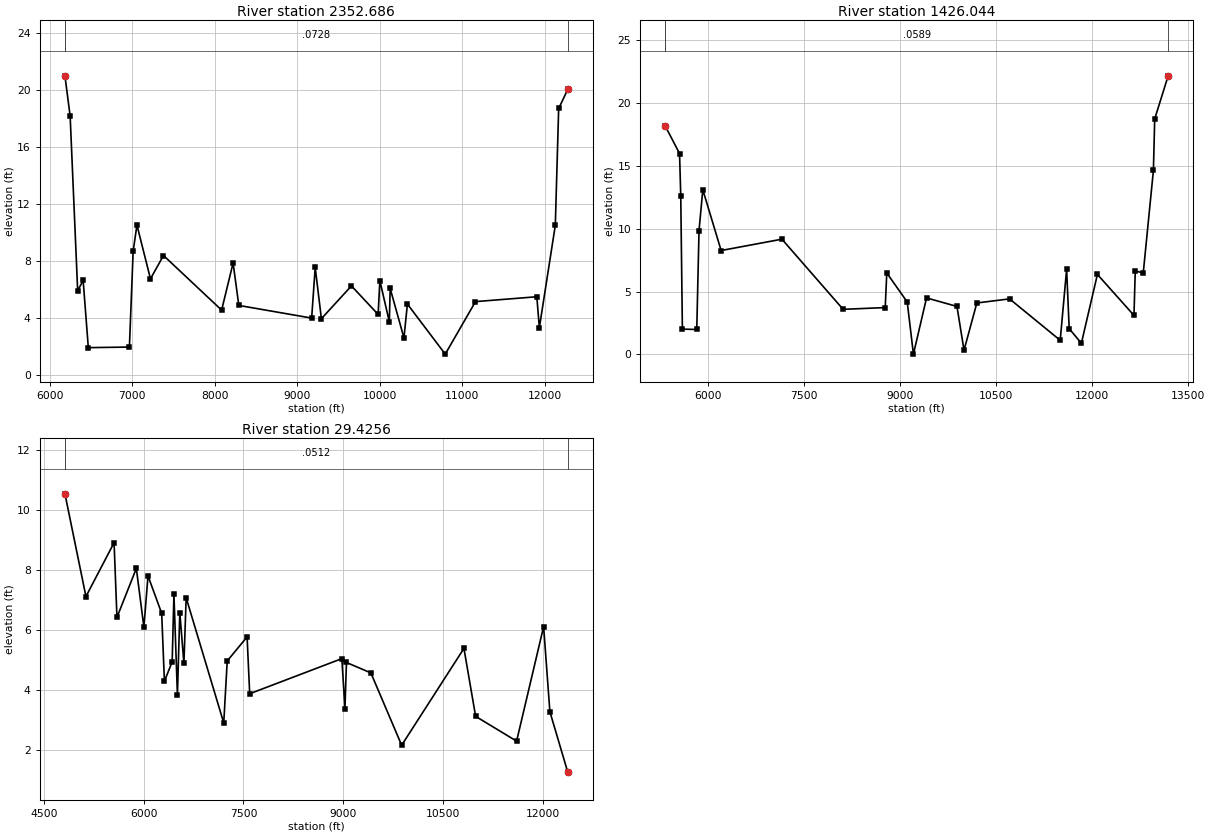
Type RM Length L Ch R = 1 ,2352.686,926.642200,926.642200,926.642200
XS GIS Cut Line= 6
687510.642934736709680.442547173687088.786089943708907.061779388
686588.276141286708352.831670538685633.415030152 707797.27611497
684279.248363465707337.206670538 682386.88725239706981.303892761
#Sta/Elev= 30
  6186.9 20.99276250.05418.164476341.1825.9184966407.5126.640007 6470.161.926833
6967.685  1.96857013.1138.6922497058.81210.525657222.7086.7539747380.539 8.38972
8084.5224.5578748223.3557.8676398292.7714.8877259174.7944.0000479217.6517.552769
 9292.653.9573659656.6046.257763  9979.84.25608210000.656.63134210115.33 3.73982
10125.766.07730110292.572.60830710334.274.98287210792.561.47239711158.875.155841
11901.675.49716311932.193.32180312125.5210.5074912166.2318.7014412276.2320.03758
#Mann= 3 , 0 , 0
  6186.9  0.0728       0  6186.9  0.0728       012276.23  0.0728       0
#XS Ineff= 2 , 0
       08989.524        11038.48       0
Bank Sta=6186.9,12276.23
Exp/Cntr=0.3,0.1

Type RM Length L Ch R = 1 ,1426.044,1396.618600,1396.618600,1396.618600
XS GIS Cut Line= 6
688042.986396983709390.315360248686964.758856446707921.631532088
685668.137252361706851.095559433684956.331696808 706564.63722609
681948.106122226706409.033777833681397.303919047706495.192781657
#Sta/Elev= 30
5334.97518.158045556.76615.981675575.56412.616275601.0652.0179655825.4491.989453
5860.8789.8610365919.92713.108816206.0338.2696437155.5279.1711048110.8833.592275
8768.4113.7304748792.7646.4836679111.9144.1771139208.9280.0288269413.7374.500197
9888.8283.8205969998.9840.33752810199.274.09763510709.954.42315811500.981.127877
11601.126.77473611641.172.05950611831.42 0.8888212081.756.36640912652.753.109653
12672.996.66065112797.38 6.4696212956.3914.6401612976.6418.7373813186.8622.16406
#Mann= 3 , 0 , 0
5334.975  0.0589       05334.975  0.0589       013186.86  0.0589       0
#XS Ineff= 2 , 0
       09345.918        10820.87       0
Bank Sta=5334.975,13186.86
Exp/Cntr=0.3,0.1

Type RM Length L Ch R = 1 , 29.4256,0.000000,0.000000,0.000000
XS GIS Cut Line= 6
688298.345585704708396.234448314687985.845585704707649.706670538
 686417.30727008706321.600991279684312.571127534705223.067156494
683548.788751572704385.987565383682475.524862707704179.043120936
#Sta/Elev= 30
 4817.1710.539535132.8927.1206015555.6838.9118815599.0466.425645 5890.318.057831
6003.8196.0991186065.5017.8072336271.2736.5606086312.2314.2982136428.9134.946868
6455.1867.1939486507.7323.836514 6543.546.5869786605.2234.8921086639.0997.078573
7203.9752.9104467256.2774.9753487554.9285.7761517593.8823.8832518979.1575.052318
9025.1833.3798259048.1964.9238189414.9854.5770349877.812 2.1682710813.885.392857
10989.493.12997611605.27 2.3047412011.266.11670812105.463.28512712374.071.273118
#Mann= 3 , 0 , 0
 4817.17  0.0512       0 4817.17  0.0512       012374.07  0.0512       0
#XS Ineff= 2 , 0
       09829.011         10209.2       0
Bank Sta=4817.17,12374.07
Exp/Cntr=0.3,0.1